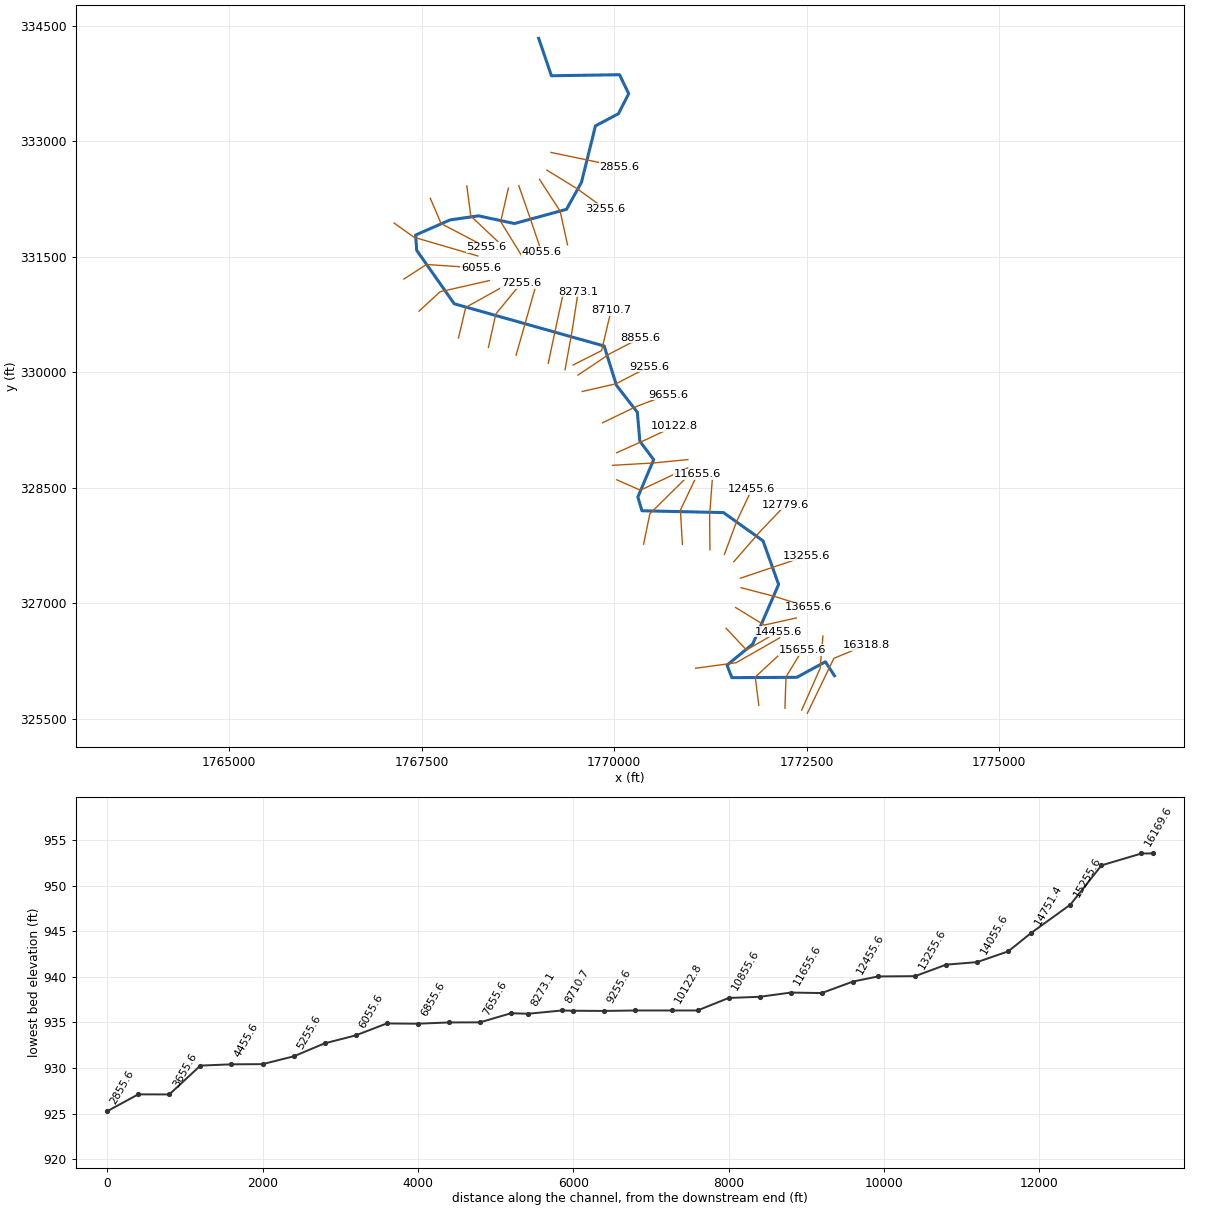
--- BthsRn1.prj (project) ---

Proj Title=BthsRn1
Current Plan=p01
Default Exp/Contr=0,0
English Units
Geom File=g01
Flow File=f01
Plan File=p01
BEGIN DESCRIPTION:
END DESCRIPTION:
DSS Export Rating Curves= 0
DSS Export Rating Curve Sorted= 0
DSS Export Volume Flow Curves= 0
DXF OffsetX= 0
DXF OffsetY= 0
DXF ScaleX= 0
DXF ScaleY= 0

--- BthsRn1.p01 (plan) ---

Plan Title=Floodplain
Program Version=4.00
Geom File=g01
Flow File=f01
K Sum by GR=0
Std Step Tol=0.01
Critical Tol=0.01
Num of Std Step Trials=20
Max Error Tol=0.3
Flow Tol Ratio=0.001
Split Flow NTrial=30
Split Flow Tol=0.02
Split Flow Ratio=0.02
Log Output Level=0
Friction Slope Method=1
Unsteady Friction Slope Method=2
Unsteady Bridges Friction Slope Method=1
Global Log Level=0
CheckData=False
Run HTab=0
Run UNet=0
Run PostProcess=0
UNET Theta=0
UNET Theta Warmup=0
UNET ZTol=0
UNET ZSATol=0
UNET MxIter=0
UNET MaxInSteps=0
UNET DtIC=0
UNET DtMin=0
UNET MaxCRTS=0
UNET WFStab=0
UNET SFStab=0
UNET WFX=0
UNET SFX=0
UNET DSS MLevel=0
UNET DZMax Abort=0
UNET Convert EG Bridges=0
UNET Use Existing IB Tables=0
UNET Froude Limit=0
UNET Froude Power=0
Write IC File=0
Echo Input=False
Echo Output=False
Write Detailed=0

--- BthsRn1.f01 (steady flow) ---

Flow Title=NFF Regression Equation
Program Version=4.00
Number of Profiles=1
Profile Names=P100yr
River Rch & RM=BthsRn1,Main      ,16318.8
3825.243
River Rch & RM=BthsRn1,Main      ,14751.4
3837.578
River Rch & RM=BthsRn1,Main      ,14455.6
5639.261
River Rch & RM=BthsRn1,Main      ,12455.6
5693.804
River Rch & RM=BthsRn1,Main      ,55.6
6290.537
River Rch & RM=BthsRn1,Main      ,55.6
6292.490
Boundary for River Rch & Prof#=BthsRn1,Main      ,1
Up Type=0
Dn Type=3
Dn Slope=0.002468

--- BthsRn1.g01 (geometry) ---

Geom Title=USGS 3m DEM
Program Version=4.00

River Reach=BthsRn1         ,Main
Reach XY= 30
     1772860.137      326060.075     1772741.959      326242.214
     1772371.467      326040.154     1771526.918      326035.946
     1771464.317      326198.914     1771798.319       326472.44
     1772134.191      327246.041     1771932.299      327811.987
     1771418.339      328179.526     1770359.332      328203.218
     1770306.434      328381.623     1770511.655      328867.224
     1770332.503      329105.537     1770299.257      329482.968
     1770029.164      329830.987     1769868.931      330342.524
     1767921.946       330891.26     1767434.329      331585.166
     1767420.179      331784.213     1767868.456      331980.762
     1768235.921      332033.487     1768703.309      331933.389
     1769379.694      332118.094     1769574.329      332469.194
     1769755.506      333201.297      1770054.34      333359.976
     1770187.236      333619.483      1770068.34      333866.243
     1769183.955      333852.717     1769018.276      334338.692

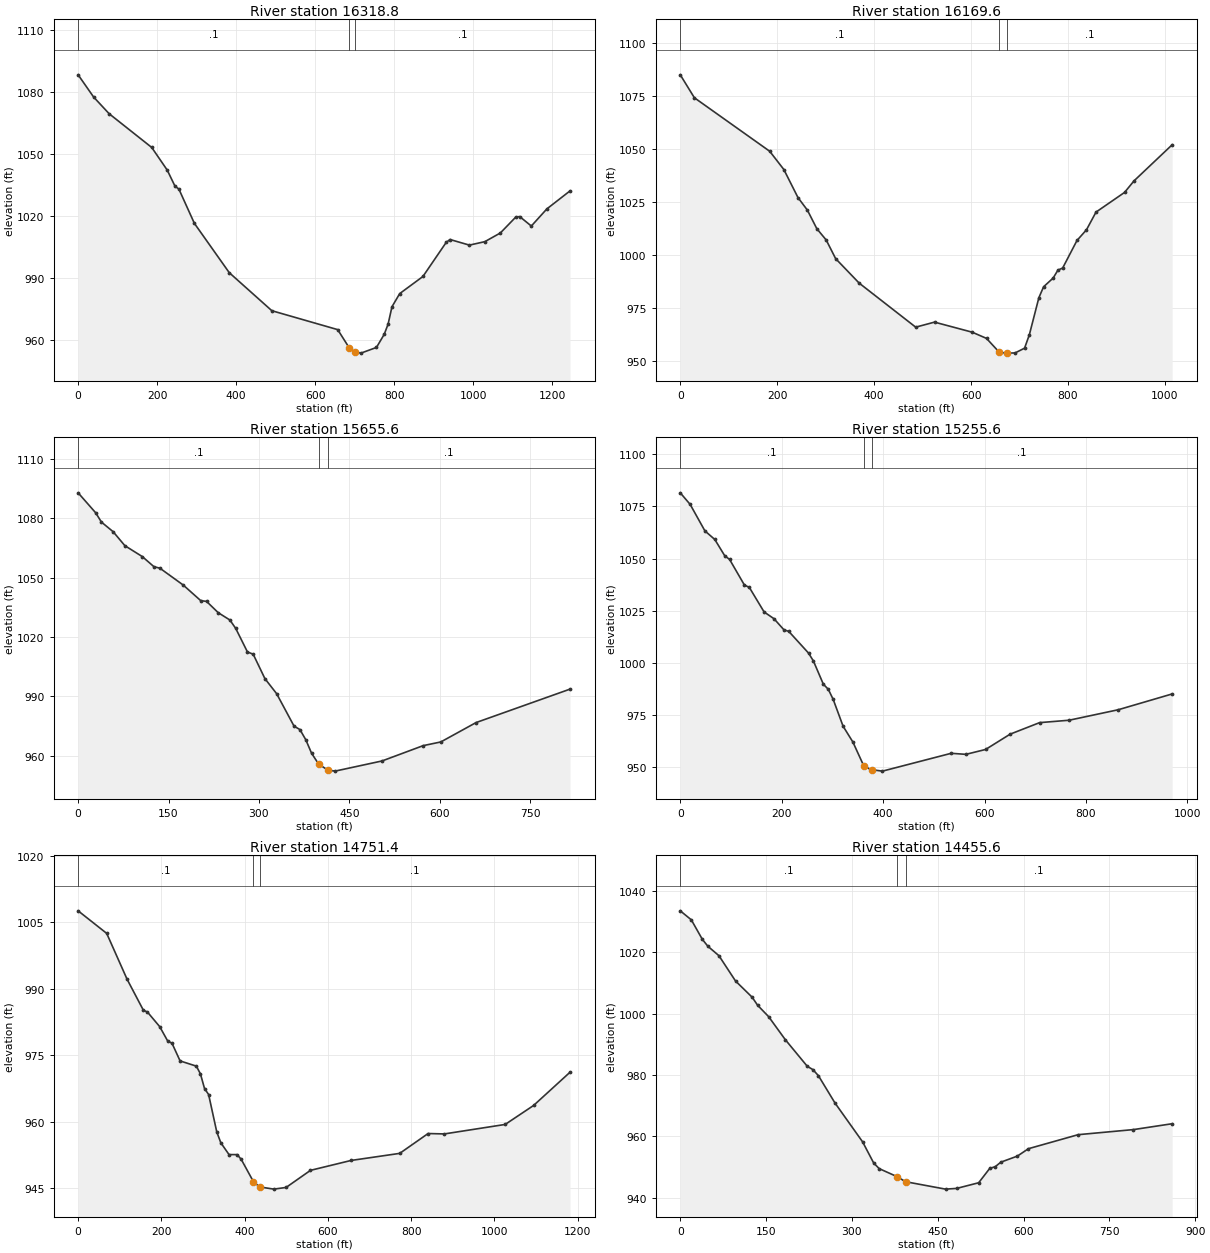
Type RM Length L Ch R = 1 ,16318.8 ,142.172,149.201,156.23
XS GIS Cut Line= 3
     1772507.034      325571.859        1772852.      326286.962
     1773268.332      326459.238
#Sta/Elev= 30
       0 1088.43    39.2 1077.66    78.4 1069.58   186.2 1053.22   225.4 1042.25
     245 1034.47   254.9 1033.05   294.1 1016.43   382.3  992.53   490.1  974.08
   656.7  964.91   685.4  956.23   700.4  954.09   715.5  953.52   754.8  956.28
   774.4  962.64   784.2  967.55     794  975.99   813.6  982.38   872.3  990.67
   931.1 1007.17   940.9  1008.6   989.9 1005.88    1029 1007.56  1068.2 1011.76
  1107.4  1019.5  1117.2 1019.71  1146.6 1015.13  1185.8 1023.42  1244.5 1032.17
#Mann= 3 , 0 , 0
       0      .1       0   685.4    .045       0   700.4      .1       0
Bank Sta=685.4,700.4
XS Rating Curve= 0 ,0
Exp/Cntr=0.3,0.1

Type RM Length L Ch R = 1 ,16169.6 ,512.634,514.031,502.732
XS GIS Cut Line= 3
     1772433.939      325614.136      1772673.17      326156.191
     1772709.897       326576.89
#Sta/Elev= 30
       0 1085.03    29.1 1074.19   184.5 1048.91   213.7 1040.27   242.8 1027.03
   262.3 1021.07   281.7 1012.32   301.1 1006.96   320.5  998.18   369.1  986.59
   485.7  965.78   524.5  968.16   602.3   963.4   631.8  960.47   658.2  953.91
   673.2  953.51   690.7   953.6   710.3  955.85   720.2  962.22   739.8   979.7
   749.6  984.88   769.3     989   779.1  992.73   788.9  993.73   818.4 1006.74
     838 1011.79   857.7 1020.16   916.6 1029.46   936.2 1034.94  1014.8 1051.98
#Mann= 3 , 0 , 0
       0      .1       0   658.2    .045       0   673.2      .1       0
Bank Sta=658.2,673.2
XS Rating Curve= 0 ,0
Exp/Cntr=0.3,0.1

Type RM Length L Ch R = 1 ,15655.6 ,396.45,400,384.99
XS GIS Cut Line= 3
     1772216.726      325638.242     1772230.046      326044.787
     1772442.846      326394.634
#Sta/Elev= 30
       0 1092.78    29.1  1082.7    38.7 1077.99    58.1 1073.14    77.5  1066.1
   106.5 1060.57   125.9 1055.44   135.6 1054.73   174.3 1046.22   203.4 1038.33
   213.1 1037.94   232.4 1032.25   251.8 1028.54   261.5 1024.29   280.9 1012.43
   290.5 1011.25   309.9  998.94   329.3  991.36   358.3  974.92     368  973.21
   377.7  968.09   387.4  961.21   399.3  955.67   414.3  952.78   426.3  952.21
   504.3  957.35   572.5  965.08   601.8  966.95   660.3  976.74   816.2  993.63
#Mann= 3 , 0 , 0
       0      .1       0   399.3    .045       0   414.3      .1       0
Bank Sta=399.3,414.3
XS Rating Curve= 0 ,0
Exp/Cntr=0.3,0.1

Type RM Length L Ch R = 1 ,15255.6 ,533.485,504.104,503.428
XS GIS Cut Line= 3
      1771876.89      325676.673     1771830.856      326043.401
      1772270.57       326452.06
#Sta/Elev= 30
       0 1081.56    19.5 1075.99    48.6 1063.27    68.1 1059.15    87.5  1051.4
    97.3 1049.55   126.4  1037.3   136.2 1036.12   165.3 1024.34   184.8  1021.1
   204.3  1015.8     214    1015   252.9  1004.6   262.6 1000.76   282.1  989.66
   291.8  987.23   301.5  982.37     321  969.49   340.4  961.86   362.1  950.28
   377.1   948.6   398.7  947.91   534.2  956.47   563.2  955.97     602  958.31
   650.4  965.66   708.5   971.2   766.6  972.35   863.4  977.38   969.9  984.98
#Mann= 3 , 0 , 0
       0      .1       0   362.1    .045       0   377.1      .1       0
Bank Sta=362.1,377.1
XS Rating Curve= 0 ,0
Exp/Cntr=0.3,0.1

Type RM Length L Ch R = 1 ,14751.4 ,327.258,295.896,358.622
XS GIS Cut Line= 3
     1771057.463      326157.756     1771581.468      326229.537
     1772148.542      326552.554
#Sta/Elev= 30
       0 1007.63    68.6 1002.54   117.5   992.2   156.7  985.19   166.5  984.78
   195.9  981.49   215.5  978.18   225.3  977.77   244.9  973.75     284  972.57
   293.8  970.82   303.6  967.51   313.4  966.17     333  957.72   342.8  955.26
   362.4  952.61     382   952.6   391.8  951.52   421.2  946.47   436.2   945.3
   470.1  944.81   499.5  945.19   558.1  949.05   655.5  951.28   772.4  952.88
   840.6  957.36   879.6  957.27  1025.7  959.41  1093.9  963.69  1181.5   971.2
#Mann= 3 , 0 , 0
       0      .1       0   421.2    .045       0   436.2      .1       0
Bank Sta=421.2,436.2
XS Rating Curve= 0 ,0
Exp/Cntr=0.3,0.1

Type RM Length L Ch R = 1 ,14455.6 ,393.953,400,333.768
XS GIS Cut Line= 3
     1771452.376      326677.053     1771716.712      326395.289
     1772127.007      326631.513
#Sta/Elev= 30
       0 1033.56    19.3 1030.62    38.6 1024.25    48.3 1021.99    67.6 1018.92
    96.6 1010.67   125.6 1005.39   135.2 1002.76   154.5  999.03   183.5  991.56
   222.1  982.83   231.8  981.78   241.5  979.78   270.4  970.89   318.7  958.21
   338.1   951.3   347.7  949.48   378.8  946.87   393.8  945.21   463.6  942.79
     483  943.02   521.6  944.87   540.9  949.55   550.6  950.12   560.3  951.58
   589.2  953.56   608.6  955.98   695.5  960.55   792.2  962.21   859.8  964.12
#Mann= 3 , 0 , 0
       0      .1       0   378.8    .045       0   393.8      .1       0
Bank Sta=378.8,393.8
XS Rating Curve= 0 ,0
Exp/Cntr=0.3,0.1

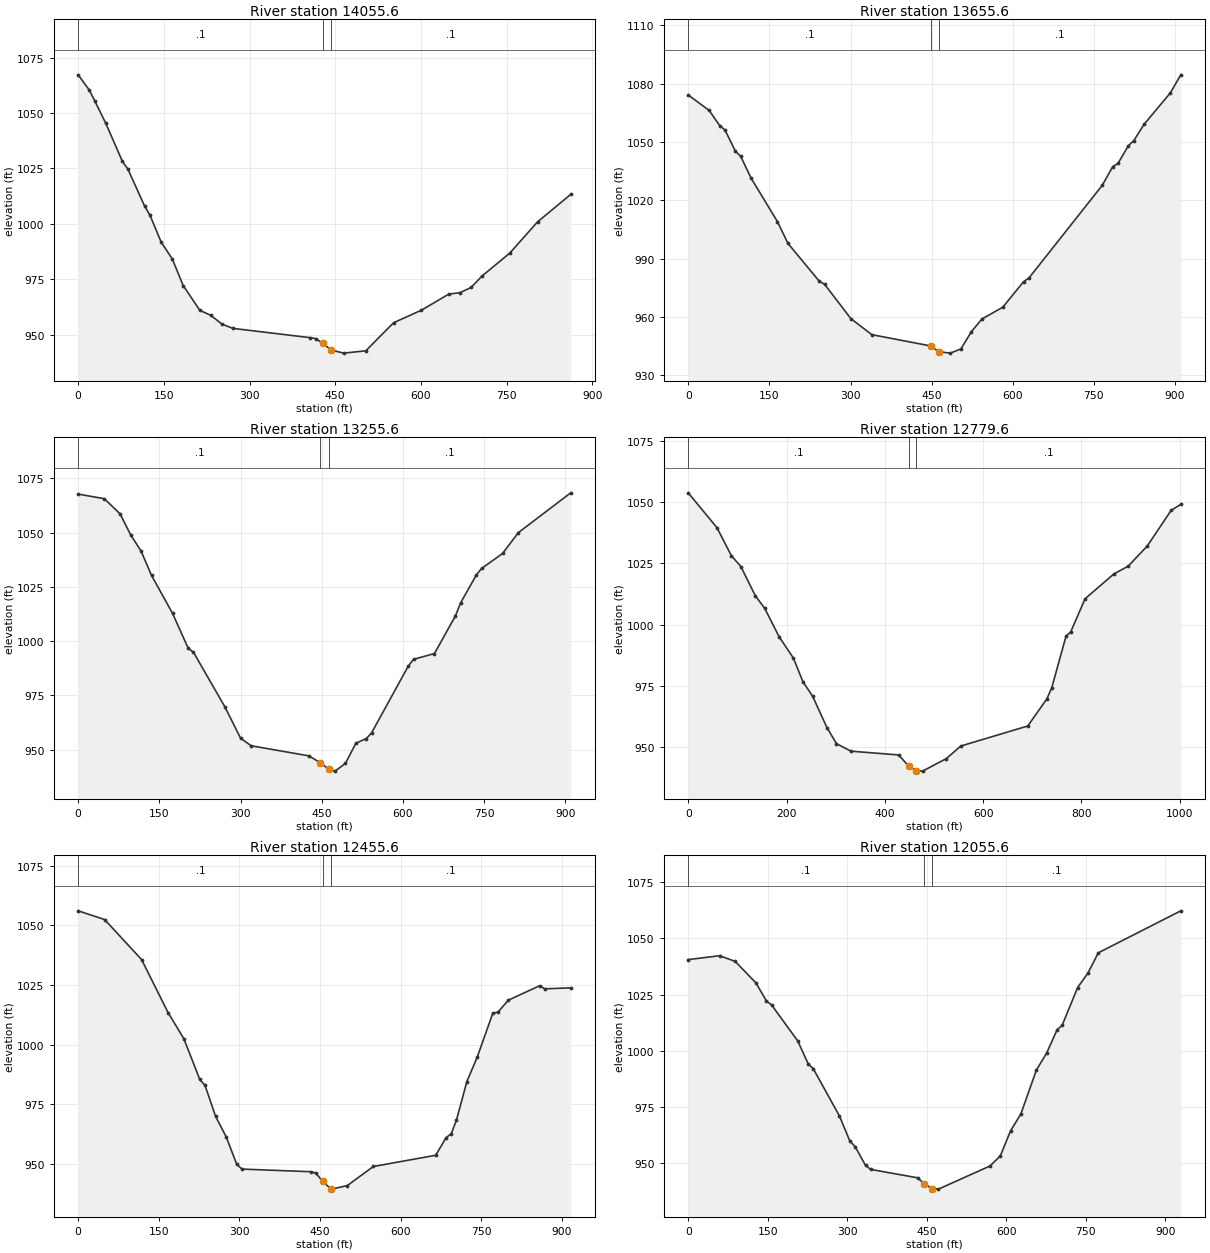
Type RM Length L Ch R = 1 ,14055.6 ,393.29,400,383.645
XS GIS Cut Line= 3
     1771576.276      326946.436     1771947.419      326718.374
     1772363.886      326810.967
#Sta/Elev= 30
       0 1067.23    19.4 1060.37      29 1055.49    48.4 1045.32    77.4 1028.19
    87.1 1024.65   116.2 1008.04   125.8 1003.79   145.2  991.78   164.6  984.18
   183.9  972.08     213  960.93   232.3  958.65   251.7   954.7     271  952.77
   406.6  948.58   416.3  948.16   428.1  945.97   443.1  943.02   464.7  941.61
   503.5  942.65     552   955.3   600.5  960.95   648.9  968.27   668.3  968.88
   687.7  971.24   707.1  976.44   755.6  986.78   804.1 1000.84   862.2 1013.25
#Mann= 3 , 0 , 0
       0      .1       0   428.1    .045       0   443.1      .1       0
Bank Sta=428.1,443.1
XS Rating Curve= 0 ,0
Exp/Cntr=0.3,0.1

Type RM Length L Ch R = 1 ,13655.6 ,386.884,400,414.373
XS GIS Cut Line= 3
     1771647.183      327203.667     1772088.151      327089.212
     1772521.451      326950.547
#Sta/Elev= 30
       0  1074.2    38.8 1066.23    58.2 1058.42    67.9  1056.2    87.2 1045.28
    96.9 1042.64   116.3 1031.35   164.8 1009.06   184.2  997.86   242.3  978.32
     252  976.79   300.5  959.13   339.3  950.84   448.1  945.04   463.1  942.06
   484.6  941.33     504  943.49   523.3  952.33   542.7  958.85   581.4  964.97
   620.1  978.17   629.8     980   765.3  1027.7   784.7 1037.32   794.4 1038.95
   813.7 1048.15   823.4 1050.61   842.8 1059.16   891.2 1075.29   910.5 1084.59
#Mann= 3 , 0 , 0
       0      .1       0   448.1    .045       0   463.1      .1       0
Bank Sta=448.1,463.1
XS Rating Curve= 0 ,0
Exp/Cntr=0.3,0.1

Type RM Length L Ch R = 1 ,13255.6 ,463.996,475.929,487.862
XS GIS Cut Line= 3
     1771638.829      327327.706     1772070.077      327472.793
     1772501.325      327617.881
#Sta/Elev= 30
       0 1067.73    48.4 1065.59    77.4 1058.63    96.8 1049.04   116.2 1041.48
   135.5 1030.25   174.3  1012.8   203.3  996.68     213  994.86   271.1  969.68
   300.1  955.23   319.5  951.76     426  947.12   447.5  943.94   462.5  941.06
   474.4  940.07   493.7  943.59   513.1  952.94   532.4  955.07   542.1   957.7
   609.9  988.47   619.6  991.58   658.3  994.26     697 1011.61   706.7 1017.67
   735.7 1030.47   745.4 1033.45   784.1 1040.36   813.2 1049.96     910 1068.31
#Mann= 3 , 0 , 0
       0      .1       0   447.5    .045       0   462.5      .1       0
Bank Sta=447.5,462.5
XS Rating Curve= 0 ,0
Exp/Cntr=0.3,0.1

Type RM Length L Ch R = 1 ,12779.6 ,315.887,324.071,330.24
XS GIS Cut Line= 3
     1771552.541      327541.806     1771904.485      327945.114
     1772227.501      328282.487
#Sta/Elev= 30
       0 1053.87    58.4 1039.63    87.6 1028.22   107.1 1023.72   136.3 1011.85
   155.7 1006.59   184.9  995.02   214.1  986.24   233.6  976.52     253  970.74
   282.2  957.88   301.7  951.28   330.9  948.21   428.2  946.66   449.1  941.99
   464.1  940.27   476.9  940.04   525.5   945.2   554.7  950.31     691   958.5
   729.9  969.61   739.6  974.01   768.8   995.2   778.5  997.06   807.7 1010.56
   866.1 1020.67   895.3 1023.87   934.2 1032.12   982.9 1046.74  1002.4 1049.15
#Mann= 3 , 0 , 0
       0      .1       0   449.1    .045       0   464.1      .1       0
Bank Sta=449.1,464.1
XS Rating Curve= 0 ,0
Exp/Cntr=0.3,0.1

Type RM Length L Ch R = 1 ,12455.6 ,391.821,400,408.252
XS GIS Cut Line= 3
     1771430.918      327637.401     1771591.608      328070.869
     1771786.759      328480.885
#Sta/Elev= 30
       0 1056.14    49.2 1052.49     118  1035.7   167.2 1013.51   196.7  1002.5
   226.2  985.48   236.1  982.93   255.7  969.98   275.4   961.4   295.1  949.85
   304.9  947.88   432.8  946.78   442.6  946.18   454.8  942.68   469.8   939.7
     472  939.48   500.9  940.99   549.2  948.97   665.2  953.67   684.5  961.02
   694.2  962.73   703.8   968.4   723.2  984.58   742.5  994.83   771.5 1013.25
   781.1  1013.7   800.4 1018.69   858.4 1024.72   868.1 1023.45   916.4 1023.85
#Mann= 3 , 0 , 0
       0      .1       0   454.8    .045       0   469.8      .1       0
Bank Sta=454.8,469.8
XS Rating Curve= 0 ,0
Exp/Cntr=0.3,0.1

Type RM Length L Ch R = 1 ,12055.6 ,398.937,400,390.254
XS GIS Cut Line= 3
     1771242.475      327697.596     1771238.382      328149.888
      1771274.69      328625.134
#Sta/Elev= 30
       0 1040.58      59 1042.32    88.5  1039.8   127.8 1030.16   147.5 1022.11
   157.3 1020.33   206.5 1004.31   226.2   994.1     236  991.84   285.2  970.83
   304.8  959.64   314.7  957.19   334.3  948.82   344.1  947.01   432.6  943.27
   444.8  940.68   459.8  938.44   471.8  938.22     569  948.53   588.5  953.02
   607.9  964.22   627.4  971.81   656.6  991.34     676  998.94   695.5 1009.23
   705.2 1011.32   734.4 1028.14   753.9 1034.62   773.3 1043.61   928.9 1062.34
#Mann= 3 , 0 , 0
       0      .1       0   444.8    .045       0   459.8      .1       0
Bank Sta=444.8,459.8
XS Rating Curve= 0 ,0
Exp/Cntr=0.3,0.1

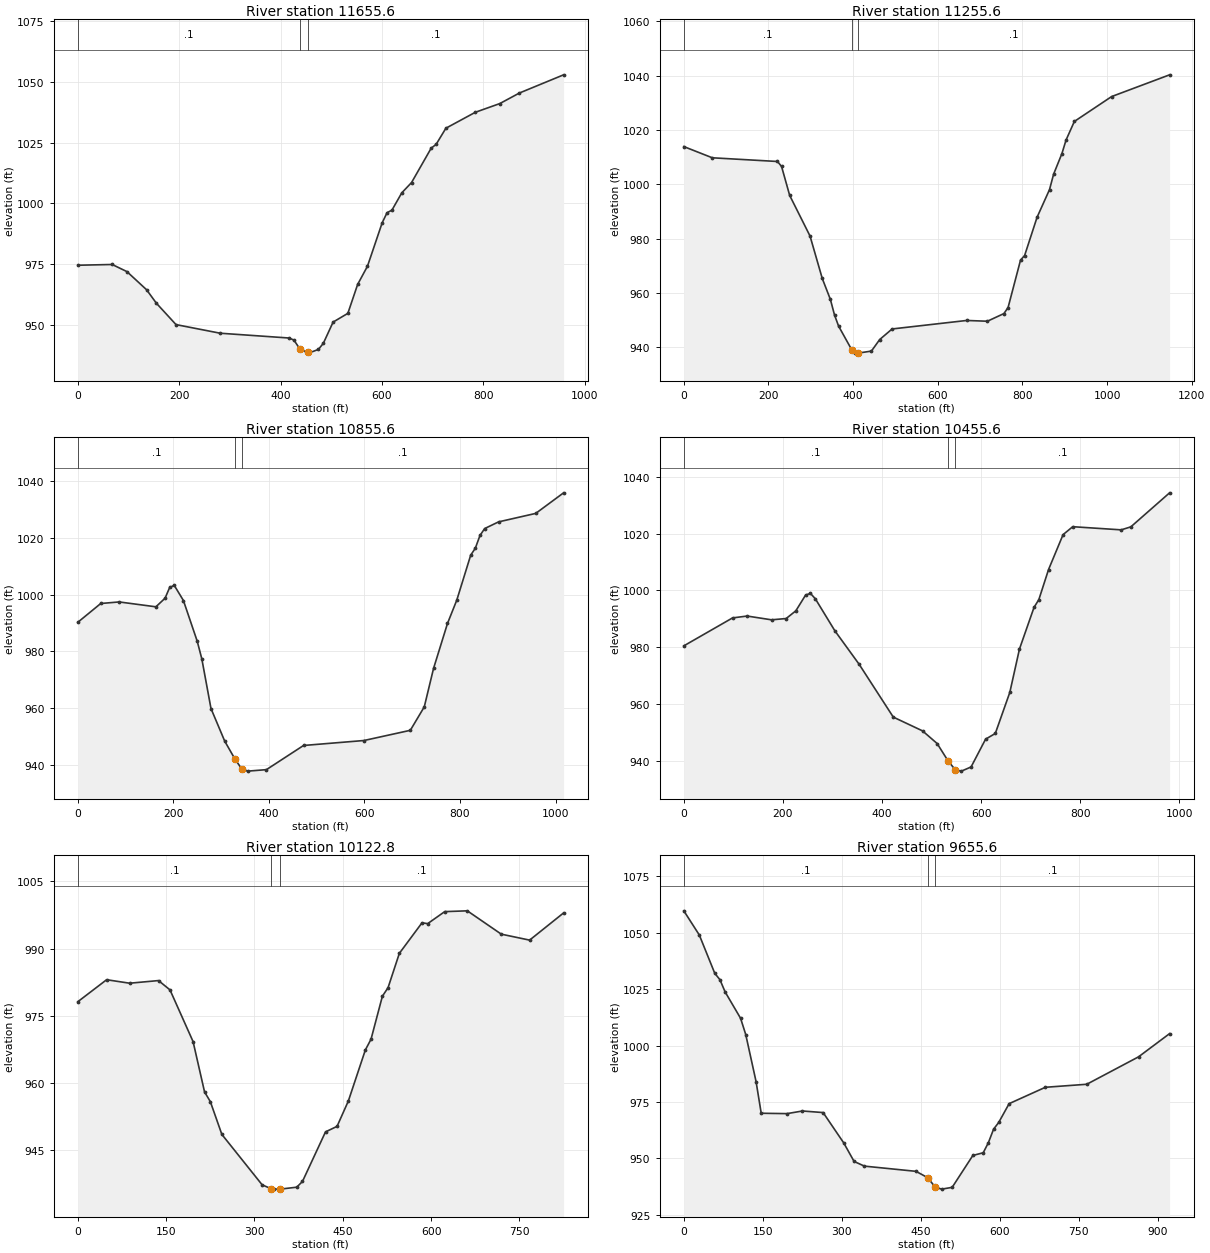
Type RM Length L Ch R = 1 ,11655.6 ,405.935,400,390.325
XS GIS Cut Line= 3
     1770884.991      327766.937     1770858.886      328211.778
     1771078.609      328674.971
#Sta/Elev= 30
       0  974.48    67.8  974.79    96.9  971.85   135.6  964.39     155  958.83
   193.7  950.02   280.9  946.47   416.5   944.5   426.2  943.67   438.1  939.98
   453.1  938.54   455.3  938.27   474.6   939.8   484.3   942.3   503.6  951.06
   532.7  954.66     552  966.57   571.4  974.08   600.4  991.96     610  996.12
   619.7  997.19   639.1 1004.31   658.4 1008.56   697.1 1022.72   706.8 1024.27
   726.1 1030.93   784.2  1037.5   832.5 1041.09   871.2 1045.44   958.3 1052.93
#Mann= 3 , 0 , 0
       0      .1       0   438.1    .045       0   453.1      .1       0
Bank Sta=438.1,453.1
XS Rating Curve= 0 ,0
Exp/Cntr=0.3,0.1

Type RM Length L Ch R = 1 ,11255.6 ,440.43,400,404.762
XS GIS Cut Line= 3
     1770380.913      327769.317     1770462.595      328165.033
      1770991.65      328687.659
#Sta/Elev= 30
       0 1013.89    67.3 1009.76   221.3  1008.4   230.9 1006.57   250.1   995.9
   298.2  980.93   327.1   965.3   346.3  957.58     356  951.87   365.6  947.78
   396.6  939.07   404.1  937.81   411.6  937.81   443.2  938.56   462.8  942.82
   492.1  946.71   668.3  949.84   717.2  949.56   756.3  952.38   766.1  954.61
   795.5  972.06   805.2  973.77   834.6  987.85     864  998.05   873.7 1003.73
   893.3 1011.31   903.1 1016.31   922.7 1023.15  1010.7 1032.31  1147.7 1040.32
#Mann= 3 , 0 , 0
       0      .1       0   396.6    .045       0   411.6      .1       0
Bank Sta=396.6,411.6
XS Rating Curve= 0 ,0
Exp/Cntr=0.3,0.1

Type RM Length L Ch R = 1 ,10855.6 ,389.282,400,382.923
XS GIS Cut Line= 3
     1770030.989      328605.503     1770338.937      328470.256
     1770954.304      328760.396
#Sta/Elev= 30
       0   990.2      48  996.83    86.5  997.38   163.4  995.66   182.6   998.7
   192.2 1002.48   201.8 1003.23     221  997.88   249.9  983.51   259.5  977.31
   278.7  959.77   307.5  948.24   328.8  941.96   343.8  938.27   355.8  937.68
   394.7   938.2   472.4  946.73   598.8  948.48   695.9  952.08   725.1  960.35
   744.5  973.91   773.7  989.79   793.1  997.99   822.3 1013.89     832 1016.35
   841.7 1020.83   851.5 1023.27   880.6 1025.63   958.4 1028.62  1016.7 1035.88
#Mann= 3 , 0 , 0
       0      .1       0   328.8    .045       0   343.8      .1       0
Bank Sta=328.8,343.8
XS Rating Curve= 0 ,0
Exp/Cntr=0.3,0.1

Type RM Length L Ch R = 1 ,10455.6 ,324.551,332.743,340.029
XS GIS Cut Line= 3
      1769977.45      328793.174     1770517.285      328824.553
      1770954.89      328867.653
#Sta/Elev= 30
       0  980.46    98.3  990.31   127.8  990.97     177  989.64   206.5  990.09
   226.1  992.81   245.8  998.37   255.6  998.95   265.5  997.04   304.8  985.79
   353.9  973.96   422.8  955.35   481.8   950.5   511.3  946.04   533.2  939.96
   548.2  936.72   560.3  936.31   579.8  937.78   609.1  947.58   628.7  949.58
     658  964.06   677.5  979.36   706.9  994.03   716.6  996.77   736.2 1007.37
   765.5 1019.67     785 1022.46   882.8 1021.35   902.3 1022.41   980.5  1034.4
#Mann= 3 , 0 , 0
       0      .1       0   533.2    .045       0   548.2      .1       0
Bank Sta=533.2,548.2
XS Rating Curve= 0 ,0
Exp/Cntr=0.3,0.1

Type RM Length L Ch R = 1 ,10122.8 ,466.581,467.257,465.953
XS GIS Cut Line= 3
     1770030.989      328957.233     1770432.965      329136.686
     1770780.275       329302.15
#Sta/Elev= 30
       0  978.15    48.9  983.06      88  982.28     137  982.87   156.5  980.79
   195.7  969.25   215.2  958.01     225  955.85   244.6  948.52     313  937.27
   328.6  936.38   332.6  936.31   343.6  936.31   371.7  936.74   381.5  938.03
   420.6  949.09   440.2  950.32   459.4  955.99   488.3  967.39   497.9  969.78
   517.2  979.38   526.8  981.28     546  988.95   584.5  995.77   594.1  995.58
     623  998.26   661.4  998.44   719.1  993.23   767.2   991.9   824.9  997.97
#Mann= 3 , 0 , 0
       0      .1       0   328.6    .045       0   343.6      .1       0
Bank Sta=328.6,343.6
XS Rating Curve= 0 ,0
Exp/Cntr=0.3,0.1

Type RM Length L Ch R = 1 ,9655.6  ,405.398,400,402.396
XS GIS Cut Line= 3
     1769849.846      329346.454     1770273.075      329551.733
     1770695.757      329712.673
#Sta/Elev= 30
       0 1059.72    29.4    1049    58.8    1032    68.6 1029.18    78.4 1023.78
   107.8 1012.07   117.6 1004.86   137.2  984.03     147  969.95     196  969.79
   225.4  970.96   264.6  970.26   303.8  956.78   323.4  948.59     343  946.51
     441   944.2   462.9  941.43   477.9  937.12     490  936.31   509.7   937.1
     549  951.24   568.7  952.44   578.5   956.9   588.4  962.91   598.2  965.91
   617.9  974.21   686.7  981.47   765.4  982.81   863.7  994.97   922.7 1005.27
#Mann= 3 , 0 , 0
       0      .1       0   462.9    .045       0   477.9      .1       0
Bank Sta=462.9,477.9
XS Rating Curve= 0 ,0
Exp/Cntr=0.3,0.1

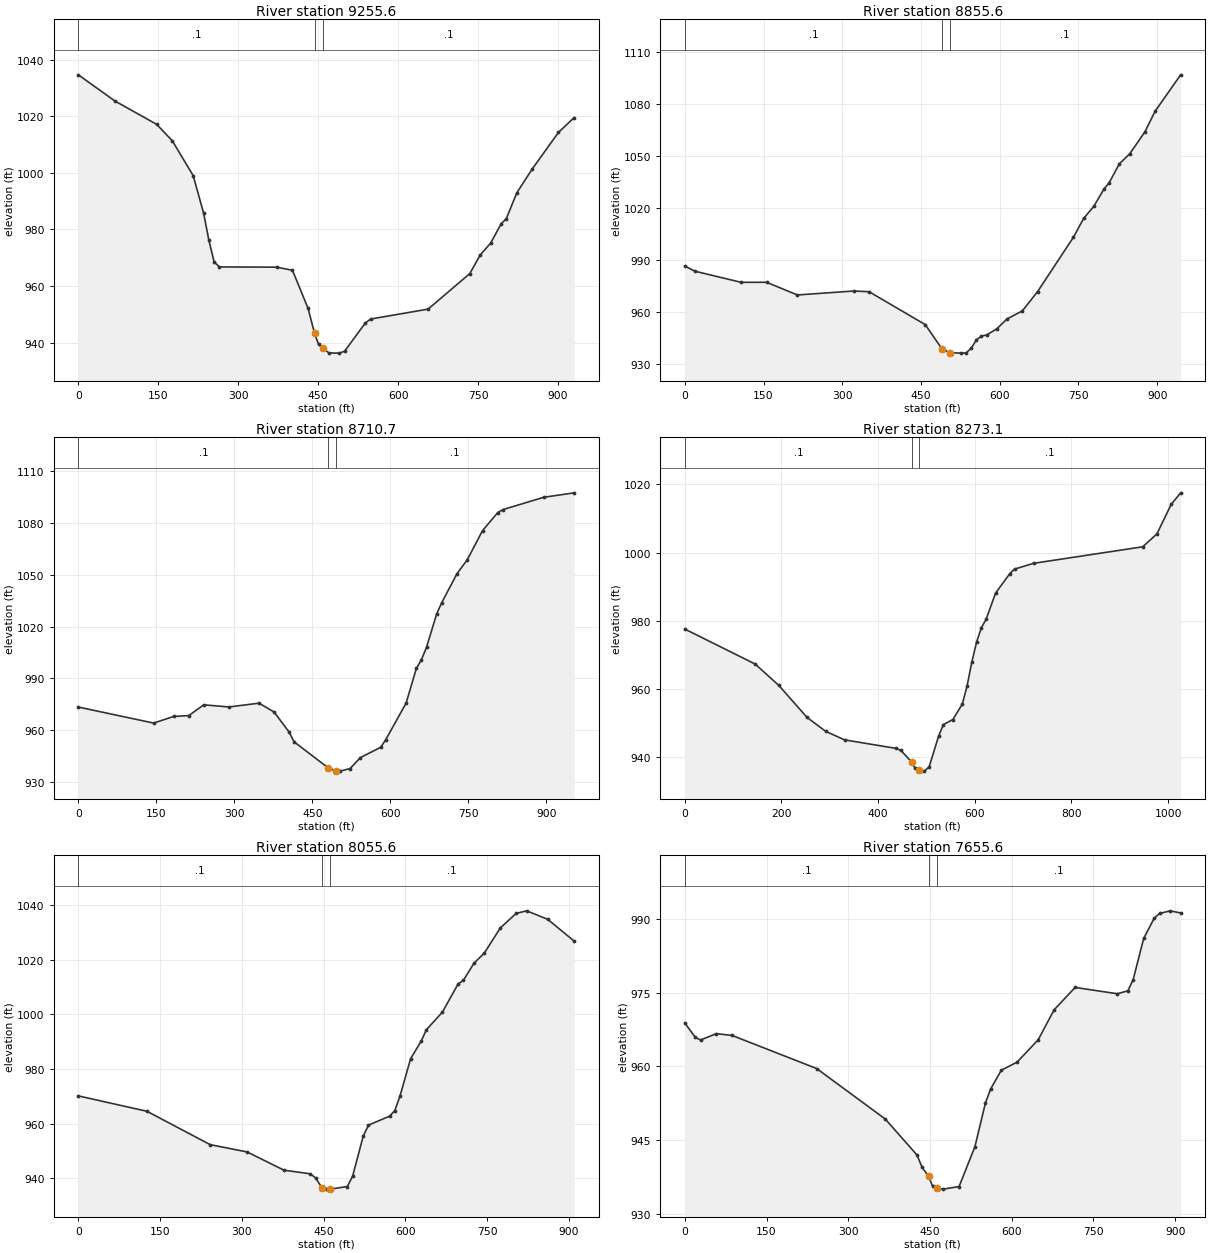
Type RM Length L Ch R = 1 ,9255.6  ,391.693,400,399.94
XS GIS Cut Line= 3
     1769584.858      329752.154     1770024.103      329853.026
     1770449.725      330073.834
#Sta/Elev= 30
       0 1034.66    68.6 1025.41     147 1017.15   176.4  1011.3   215.5  999.01
   235.1   985.7   244.9  976.16   254.7  968.56   264.5  966.74   372.3  966.65
   401.7  965.56   431.1  952.04   443.2  943.23   450.7  939.34   458.2  938.18
   470.2  936.32   489.8  936.26   499.6  936.95   538.7  946.98   548.5  948.32
   656.2  951.82   734.5  964.41     754  970.99   773.6  975.18   793.2  981.98
     803  983.83   822.5   992.9   851.9 1001.47   900.8 1014.31   930.2 1019.54
#Mann= 3 , 0 , 0
       0      .1       0   443.2    .045       0   458.2      .1       0
Bank Sta=443.2,458.2
XS Rating Curve= 0 ,0
Exp/Cntr=0.3,0.1

Type RM Length L Ch R = 1 ,8855.6  ,127.564,144.849,164.687
XS GIS Cut Line= 3
     1769529.656      329965.355     1769942.322      330242.676
     1770339.572      330448.825
#Sta/Elev= 30
       0  986.56    19.5  983.58   107.2  977.18     156  977.19   214.5  969.87
   321.7  972.15     351  971.76   458.2  952.74   489.7  938.86   504.7  936.52
   526.4  936.28   536.1  936.43   545.8  939.17   555.6   943.9   565.3  946.16
     575  946.75   594.5  950.33   613.9     956   643.1  960.67   672.3  971.86
   740.4 1003.17   759.9 1014.08   779.3 1021.08   798.8 1031.14   808.5 1034.64
     828 1045.64   847.5 1051.32   876.6 1064.04   896.1 1075.98   944.7 1097.01
#Mann= 3 , 0 , 0
       0      .1       0   489.7    .045       0   504.7      .1       0
Bank Sta=489.7,504.7
XS Rating Curve= 0 ,0
Exp/Cntr=0.3,0.1

Type RM Length L Ch R = 1 ,8710.7  ,436.763,437.58,438.397
XS GIS Cut Line= 3
     1769464.502      330096.074     1769835.118      330283.052
     1769958.657      330807.257
#Sta/Elev= 30
       0   973.4   144.8  964.13   183.4  967.97   212.4  968.46   241.3   974.7
   289.6  973.45   347.5  975.65   376.5  970.55   405.5  958.88   415.1  953.24
   480.8  938.17   495.8  936.33   503.2  936.31   522.8  937.81   542.4  944.13
   581.6   950.1   591.4  954.56   630.5  975.73   650.1  995.74   659.9 1000.74
   669.7 1008.01   689.3 1027.36   699.1 1033.91   728.5  1050.7     748 1058.63
   777.4 1075.53   806.8 1086.01   816.6 1087.71   894.9 1094.83   953.7 1097.43
#Mann= 3 , 0 , 0
       0      .1       0   480.8    .045       0   495.8      .1       0
Bank Sta=480.8,495.8
XS Rating Curve= 0 ,0
Exp/Cntr=0.3,0.1

Type RM Length L Ch R = 1 ,8273.1  ,218.239,217.571,216.792
XS GIS Cut Line= 3
     1769360.996      330035.974     1769451.146      330533.468
     1769531.279      331047.656
#Sta/Elev= 30
       0  977.61   145.8  967.33   194.5  961.09   252.8  951.72   291.7   947.6
   330.6  945.12   437.5  942.61   447.3  942.02   469.8  938.53   476.4   936.8
   484.8  936.14   495.9  935.95   505.6  937.22   525.2  946.21   535.1  949.61
   554.7  951.07   574.3  955.62   584.1  960.91     594  967.97   603.8  973.78
   613.6  977.98   623.4  980.45   643.1  988.16   672.5  993.85   682.3  995.18
   721.6  996.88   947.4 1001.72   976.9  1005.5  1006.4 1014.14    1026 1017.55
#Mann= 3 , 0 , 0
       0      .1       0   469.8    .045       0   484.8      .1       0
Bank Sta=469.8,484.8
XS Rating Curve= 0 ,0
Exp/Cntr=0.3,0.1

Type RM Length L Ch R = 1 ,8055.6  ,401.559,400,398.552
XS GIS Cut Line= 3
     1769143.021      330119.451     1769237.015      330564.643
     1769333.204      331009.358
#Sta/Elev= 30
       0  970.13   125.9   964.5     242  952.29   309.8  949.62   377.6  942.93
     426  941.61   435.6  940.07   447.5  936.41     455  936.01   462.5  936.01
   493.7  936.96   503.4  940.73   522.8  955.35   532.5  959.42   571.2  962.71
   580.9  964.78   590.5  970.17   609.9  983.77   629.3   990.2   638.9  994.38
     668 1000.73     697 1011.09   706.7 1012.43   726.1 1018.67   745.4 1022.48
   774.5  1031.6   803.5 1036.91   822.9 1037.86   861.6 1034.74     910 1026.77
#Mann= 3 , 0 , 0
       0      .1       0   447.5    .045       0   462.5      .1       0
Bank Sta=447.5,462.5
XS Rating Curve= 0 ,0
Exp/Cntr=0.3,0.1

Type RM Length L Ch R = 1 ,7655.6  ,398.646,400,389.913
XS GIS Cut Line= 3
     1768724.701      330223.811     1768849.292      330661.421
     1768973.883       331099.03
#Sta/Elev= 30
       0  968.85    19.4   965.9      29  965.39    58.1  966.68    87.1   966.3
     242  959.57   367.9  949.29     426  941.98   435.6  939.44   447.5  937.61
     455  935.55   462.5  935.16   474.4  935.01   503.4  935.54   532.4  943.62
   551.8  952.57   561.5  955.45   580.9  959.23   609.9  960.88   648.6  965.43
   677.7  971.51   716.4  976.09   793.8   974.8   813.2   975.4   822.9  977.68
   842.2  986.06   861.6  990.21   871.3  991.15   890.6  991.69     910  991.26
#Mann= 3 , 0 , 0
       0      .1       0   447.5    .045       0   462.5      .1       0
Bank Sta=447.5,462.5
XS Rating Curve= 0 ,0
Exp/Cntr=0.3,0.1

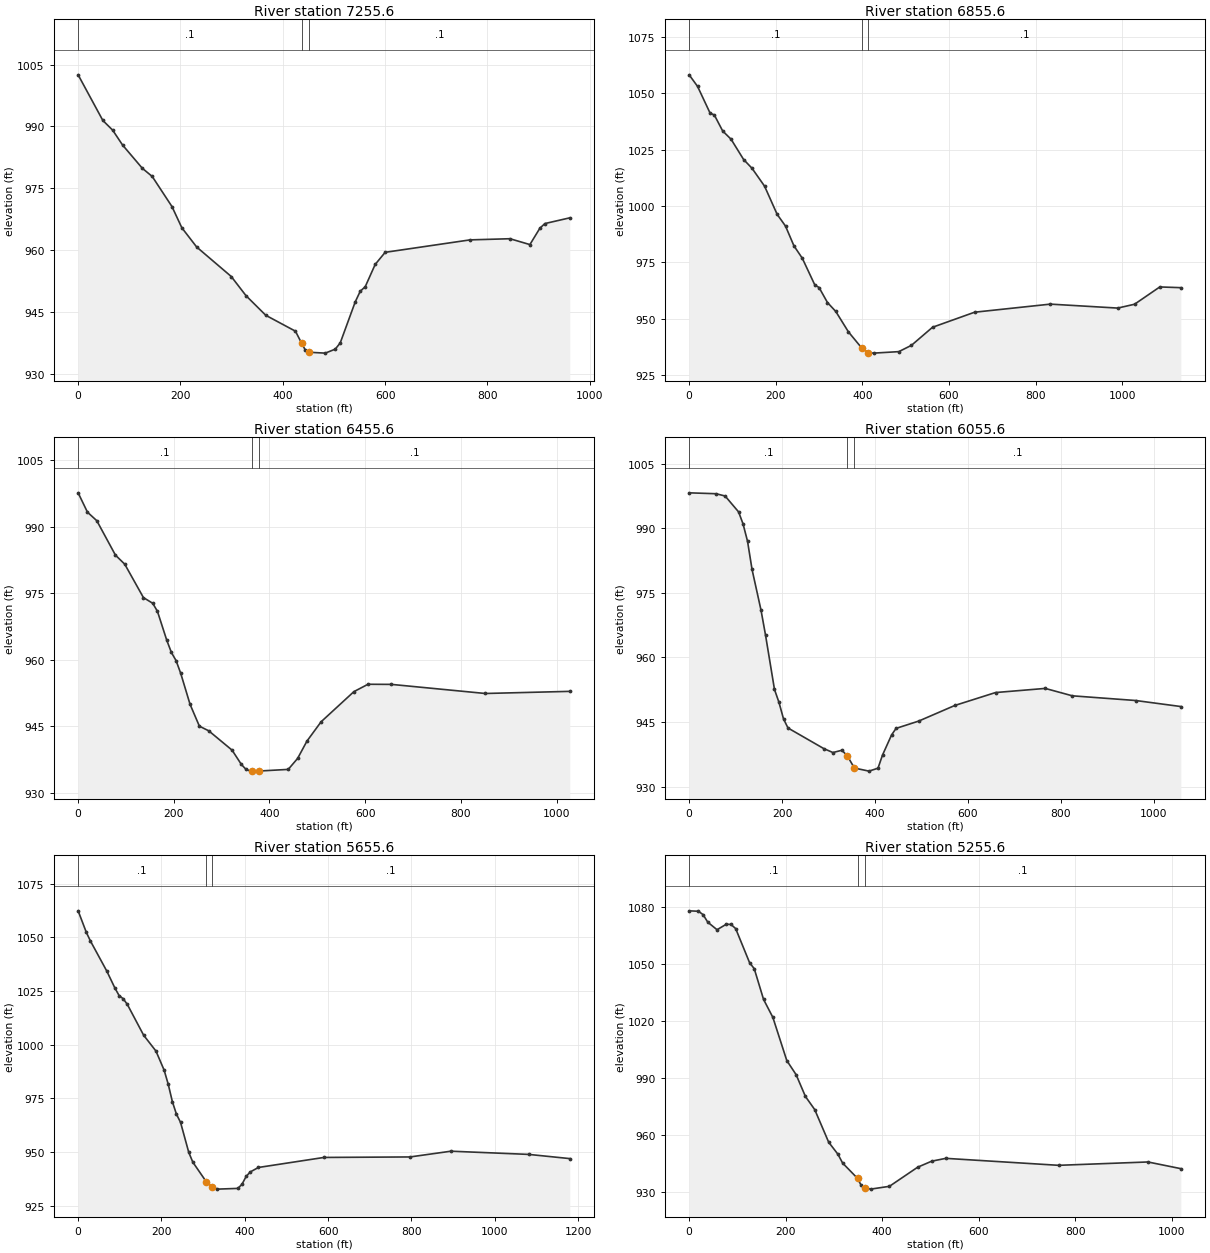
Type RM Length L Ch R = 1 ,7255.6  ,400.341,400,385.634
XS GIS Cut Line= 3
     1768365.676      330324.785      1768461.36      330758.414
     1768789.492      331157.922
#Sta/Elev= 30
       0 1002.53    48.3  991.46    67.6  989.09    86.9  985.49   125.5  979.85
   144.8  977.87   183.4  970.57   202.7  965.42   231.7  960.75   299.3  953.59
   328.2  948.93   366.8  944.18   424.8  940.32   436.6  937.46   444.1  935.73
   451.6  935.21   483.1     935   502.6  935.97   512.3  937.48   541.6  947.43
   551.4  950.02   561.1   951.1   580.6  956.52   600.1  959.46     766  962.48
     844  962.76     883  961.34   902.5  965.31   912.3  966.44     961  967.83
#Mann= 3 , 0 , 0
       0      .1       0   436.6    .045       0   451.6      .1       0
Bank Sta=436.6,451.6
XS Rating Curve= 0 ,0
Exp/Cntr=0.3,0.1

Type RM Length L Ch R = 1 ,6855.6  ,413.382,400,399.142
XS GIS Cut Line= 3
     1767977.066      330448.504     1768070.655       330844.06
      1768707.61      331198.698
#Sta/Elev= 30
       0 1058.11    19.4 1052.99    48.4 1041.13    58.1 1040.34    77.4 1033.25
    96.8 1029.59   125.8  1020.6   145.2 1016.72   174.2 1008.79   203.2  996.33
   222.6   991.1     242  982.37   261.3  976.88   290.3  965.02     300  963.92
   319.4  957.27   338.7   953.3   367.8  944.28     399  937.03     414  935.02
   425.9  934.86   484.2  935.52   513.4  938.32     562  946.31   659.2  952.98
   834.2  956.56   989.7  954.81  1028.6  956.51  1086.9  964.17  1135.5  963.85
#Mann= 3 , 0 , 0
       0      .1       0     399    .045       0     414      .1       0
Bank Sta=399,414
XS Rating Curve= 0 ,0
Exp/Cntr=0.3,0.1

Type RM Length L Ch R = 1 ,6455.6  ,403.894,400,392.28
XS GIS Cut Line= 3
     1767465.183        330795.7     1767737.332      331047.118
      1768378.22      331193.001
#Sta/Elev= 30
       0  997.62    19.5  993.26      39  991.34      78  983.58    97.5  981.53
   136.5  974.01     156  972.72   165.8  970.91   185.3  964.39     195  961.63
   204.8  959.79   214.5  956.92     234  949.94   253.5  945.02     273  943.98
   321.8  939.62   341.3  936.39     351  935.28   360.8  934.89     363   934.9
     378  934.91   439.2  935.28   458.8  937.75   478.4  941.67   507.9  946.01
   576.5  952.81     606  954.47     655  954.44   851.2  952.39  1027.8  952.87
#Mann= 3 , 0 , 0
       0      .1       0     363    .045       0     378      .1       0
Bank Sta=363,378
XS Rating Curve= 0 ,0
Exp/Cntr=0.3,0.1

Type RM Length L Ch R = 1 ,6055.6  ,427.18,400,397.522
XS GIS Cut Line= 3
     1767268.145      331212.576     1767560.481      331401.642
     1768269.202      331354.509
#Sta/Elev= 30
       0  998.25      58  998.04    77.4  997.51   106.4  993.82     116  991.03
   125.7  986.98   135.4  980.44   154.7  970.98   164.4  965.19   183.7  952.55
   193.4  949.54   203.1  945.72   212.8   943.6   290.1   938.8   309.5   937.9
   328.8  938.43   340.6  937.12   355.6   934.3   387.1  933.58   406.5  934.26
   416.3  937.33   435.7  941.98   445.4  943.51   494.1  945.21   571.9  948.84
   659.5  951.84   766.5   952.8   824.9  951.08   961.1  949.99  1058.4  948.59
#Mann= 3 , 0 , 0
       0      .1       0   340.6    .045       0   355.6      .1       0
Bank Sta=340.6,355.6
XS Rating Curve= 0 ,0
Exp/Cntr=0.3,0.1

Type RM Length L Ch R = 1 ,5655.6  ,412.378,400,397.022
XS GIS Cut Line= 3
     1767142.429      331938.735     1767398.414       331755.72
     1768228.825       331511.98
#Sta/Elev= 30
       0 1062.35    19.7 1052.32    29.5 1048.31    68.8 1034.28    88.5 1026.29
    98.3  1022.9   108.2 1021.39     118 1018.79   157.3 1004.39   186.8  997.03
   206.5   988.1   216.3  981.54   226.2  973.46     236  967.61   245.8  963.83
   265.5  949.86   275.3  945.27   307.2  936.26   322.2  933.77   334.3  932.71
   383.5  933.05   393.4  935.01   403.2   938.6     413   940.7   432.7   942.8
     590  947.47   796.6   947.7   894.9  950.38  1081.8  948.88  1180.1  946.93
#Mann= 3 , 0 , 0
       0      .1       0   307.2    .045       0   322.2      .1       0
Bank Sta=307.2,322.2
XS Rating Curve= 0 ,0
Exp/Cntr=0.3,0.1

Type RM Length L Ch R = 1 ,5255.6  ,406.164,400,394.807
XS GIS Cut Line= 3
     1767610.956       332260.79     1767751.214      331932.887
     1768337.843      331625.036
#Sta/Elev= 30
       0 1078.22    19.3 1077.99    28.9  1076.2    38.6 1072.22    57.8 1068.24
    77.1 1071.16    86.8 1071.01    96.4 1068.85   125.3 1050.81   134.9 1047.68
   154.2 1031.46   173.5 1021.96   202.4  999.16   221.7  991.71     241  980.21
   260.3  973.26   289.2  956.05   308.4  949.69   318.1  945.04   349.1  936.93
   356.6  933.24   364.1  932.05   376.1  931.28   415.1  932.76   473.6  942.85
   502.8  946.04     532  947.53   765.8  943.85   950.9  945.62  1019.1  942.09
#Mann= 3 , 0 , 0
       0      .1       0   349.1    .045       0   364.1      .1       0
Bank Sta=349.1,364.1
XS Rating Curve= 0 ,0
Exp/Cntr=0.3,0.1

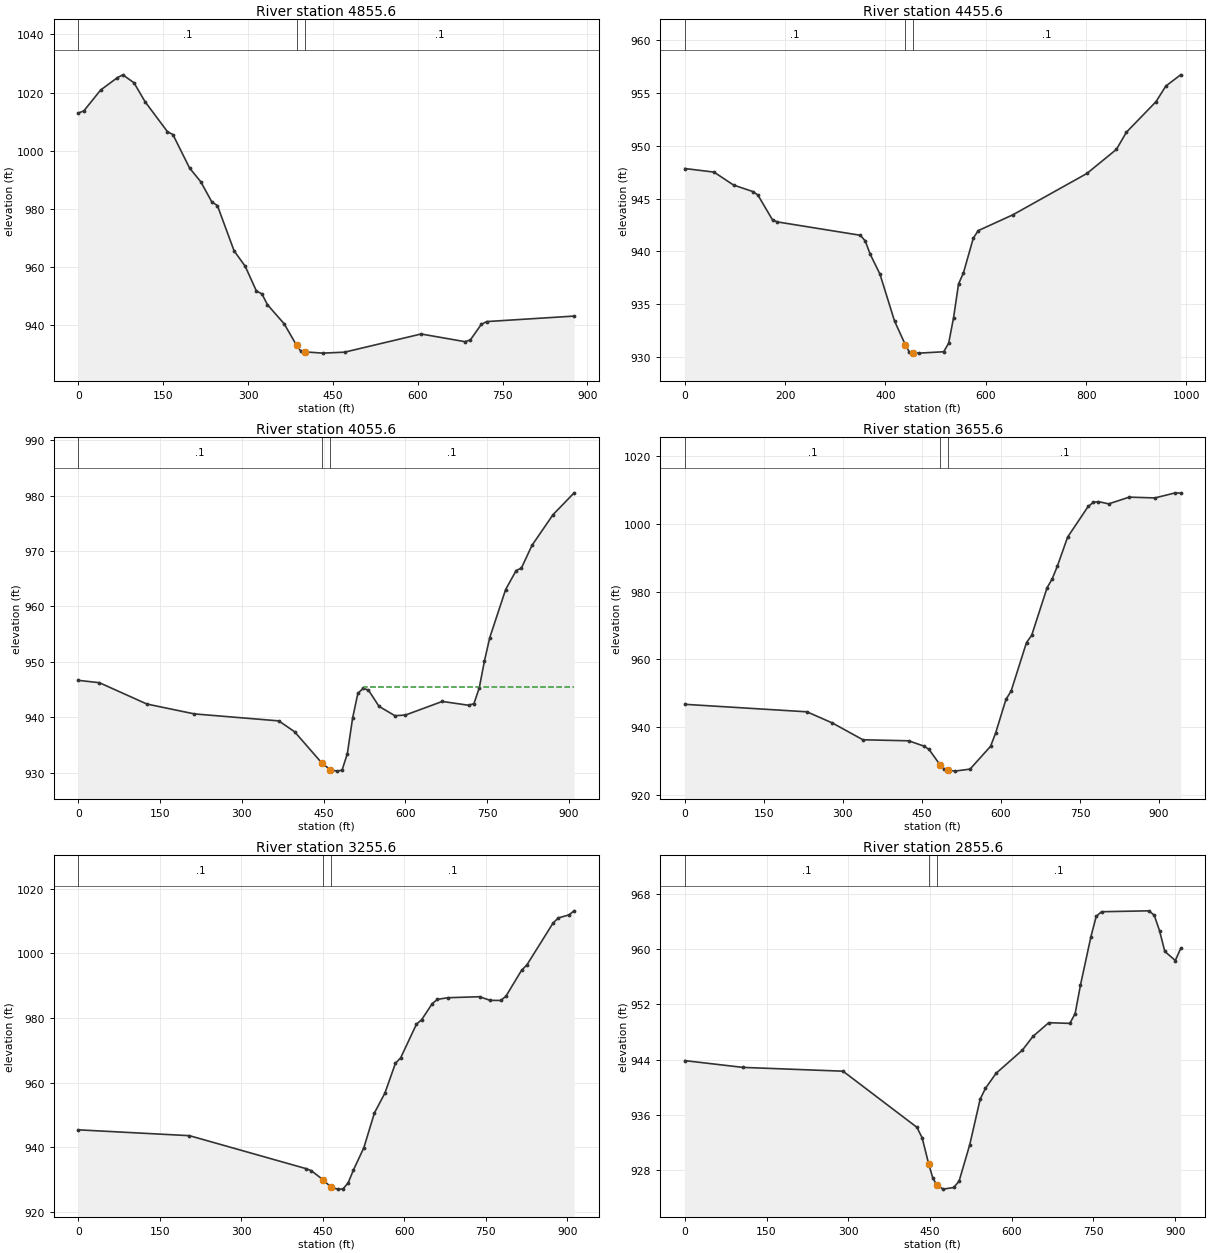
Type RM Length L Ch R = 1 ,4855.6  ,407.908,400,404.97
XS GIS Cut Line= 3
     1768085.215      332421.309     1768136.486      332031.207
     1768487.687      331699.284
#Sta/Elev= 30
       0 1012.98     9.8 1013.73    39.3 1020.87    68.9 1025.13    78.7 1026.12
    98.4 1023.39     118 1016.88   157.4 1006.62   167.2 1005.58   196.7  994.08
   216.4  989.38   236.1  982.41   245.9  981.17   275.4  965.61   295.1  960.28
   314.8  951.81   324.6  950.81   334.4  947.08   363.9  940.53     386  933.09
   393.5  931.07     401  930.86   432.1  930.43   470.8  930.76   606.1  937.01
   683.4  934.38   693.1  934.95   712.4   940.3   722.1  941.28   876.7  943.17
#Mann= 3 , 0 , 0
       0      .1       0     386    .045       0     401      .1       0
Bank Sta=386,401
XS Rating Curve= 0 ,0
Exp/Cntr=0.3,0.1

Type RM Length L Ch R = 1 ,4455.6  ,387.476,400,381.17
XS GIS Cut Line= 3
     1768624.759      332393.712     1768524.698      331957.777
     1768808.948      331497.295
#Sta/Elev= 30
       0  947.83    58.3  947.49    97.2  946.27   136.1  945.65   145.8  945.32
     175  942.97   184.7  942.79     350  941.53   359.8  940.99   369.5  939.75
   388.9  937.88   418.1  933.44   439.8  931.18   447.3  930.54   454.8  930.45
   466.9  930.41   516.1  930.54     526  931.35   535.8  933.76   545.7  936.94
   555.5  937.99   575.2  941.27     585  941.97   653.9  943.46   801.5  947.36
   860.5  949.64   880.2  951.25   939.2  954.13   958.9  955.61   988.4  956.67
#Mann= 3 , 0 , 0
       0      .1       0   439.8    .045       0   454.8      .1       0
Bank Sta=439.8,454.8
XS Rating Curve= 0 ,0
Exp/Cntr=0.3,0.1

Type RM Length L Ch R = 1 ,4055.6  ,394.248,400,397.501
XS GIS Cut Line= 3
     1768760.477      332424.412      1768909.97      331994.675
     1769056.171      331563.786
#Sta/Elev= 30
       0  946.66    38.7  946.23   125.9  942.38     213   940.6   367.9  939.34
   396.9  937.38   447.5  931.67   462.5  930.54   474.4  930.27     484  930.44
   493.7  933.42   503.4  939.86   513.1  944.34   522.8   945.2   532.4  944.91
   551.8  941.97   580.9  940.28   600.2  940.39     668  942.85   716.4  942.16
   726.1  942.46   735.8  945.29   745.4  950.19   755.1  954.37   784.2  963.04
   803.5  966.48   813.2  966.93   832.6  971.03   871.3  976.58     910  980.51
#Mann= 3 , 0 , 0
       0      .1       0   447.5    .045       0   462.5      .1       0
#XS Ineff= 2 , 0
                          523.47          945.46
Permanent Ineff=
       F       F
Bank Sta=447.5,462.5
XS Rating Curve= 0 ,0
Exp/Cntr=0.3,0.1

Type RM Length L Ch R = 1 ,3655.6  ,389.771,400,416.99
XS GIS Cut Line= 3
     1769028.829       332508.04      1769296.85      332094.774
     1769393.001      331656.815
#Sta/Elev= 30
       0  946.79   231.8  944.58   280.1  941.29     338  936.35     425  936.04
   453.9  934.47   463.6  933.49   485.1  928.82   492.6   927.7   500.1  927.42
   512.1  927.11   541.3   927.7   580.3  934.42     590  938.37   609.5  948.24
   619.3  950.69   648.5  964.99   658.3  967.09   687.5   981.1   697.3  983.77
     707  987.45   726.5  996.03   765.5 1005.06   775.2 1006.26     785 1006.49
   804.5 1005.83   843.5 1007.81   892.2 1007.58   931.2 1009.08     941 1008.99
#Mann= 3 , 0 , 0
       0      .1       0   485.1    .045       0   500.1      .1       0
Bank Sta=485.1,500.1
XS Rating Curve= 0 ,0
Exp/Cntr=0.3,0.1

Type RM Length L Ch R = 1 ,3255.6  ,392.073,400,409.59
XS GIS Cut Line= 3
     1769125.199      332626.819     1769515.236      332387.244
     1769883.963      332121.489
#Sta/Elev= 30
       0  945.46   204.5  943.65   418.8  933.47   428.5  932.84   450.2  930.03
   465.2  927.67   477.1  927.12   486.8  927.18   496.4  929.02   506.1     933
   525.4  939.96   544.8  950.68   564.1  956.83   583.5  966.06   593.1  967.73
   622.1  978.13   631.8  979.54   651.2   984.5   660.8  985.81   680.2  986.32
   738.2  986.63   757.5  985.51   776.9  985.47   786.5  986.71   815.6  994.82
   825.2  996.43   873.6 1009.44   883.2    1011   902.6 1011.93   912.3 1013.19
#Mann= 3 , 0 , 0
       0      .1       0   450.2    .045       0   465.2      .1       0
Bank Sta=450.2,465.2
XS Rating Curve= 0 ,0
Exp/Cntr=0.3,0.1

Type RM Length L Ch R = 1 ,2855.6  ,397.377,400,390.997
XS GIS Cut Line= 3
     1769178.622      332856.815     1769624.034      332763.901
     1770069.446      332670.987
#Sta/Elev= 30
       0  943.87   106.5  942.89   290.4  942.34     426  934.22   435.6   932.7
   447.5  928.95     455  926.92   462.5  925.86   474.4  925.27   493.7  925.51
   503.4  926.43   522.8  931.65   542.1  938.29   551.8  939.86   571.2  942.03
   619.6  945.39   638.9  947.37     668  949.36   706.7  949.26   716.4  950.68
   726.1  954.77   745.4  961.82   755.1  964.75   764.8  965.42   851.9  965.55
   861.6  964.91   871.3  962.67     881  959.67   900.3  958.36     910   960.1
#Mann= 3 , 0 , 0
       0      .1       0   447.5    .045       0   462.5      .1       0
Bank Sta=447.5,462.5
XS Rating Curve= 0 ,0
Exp/Cntr=0.3,0.1