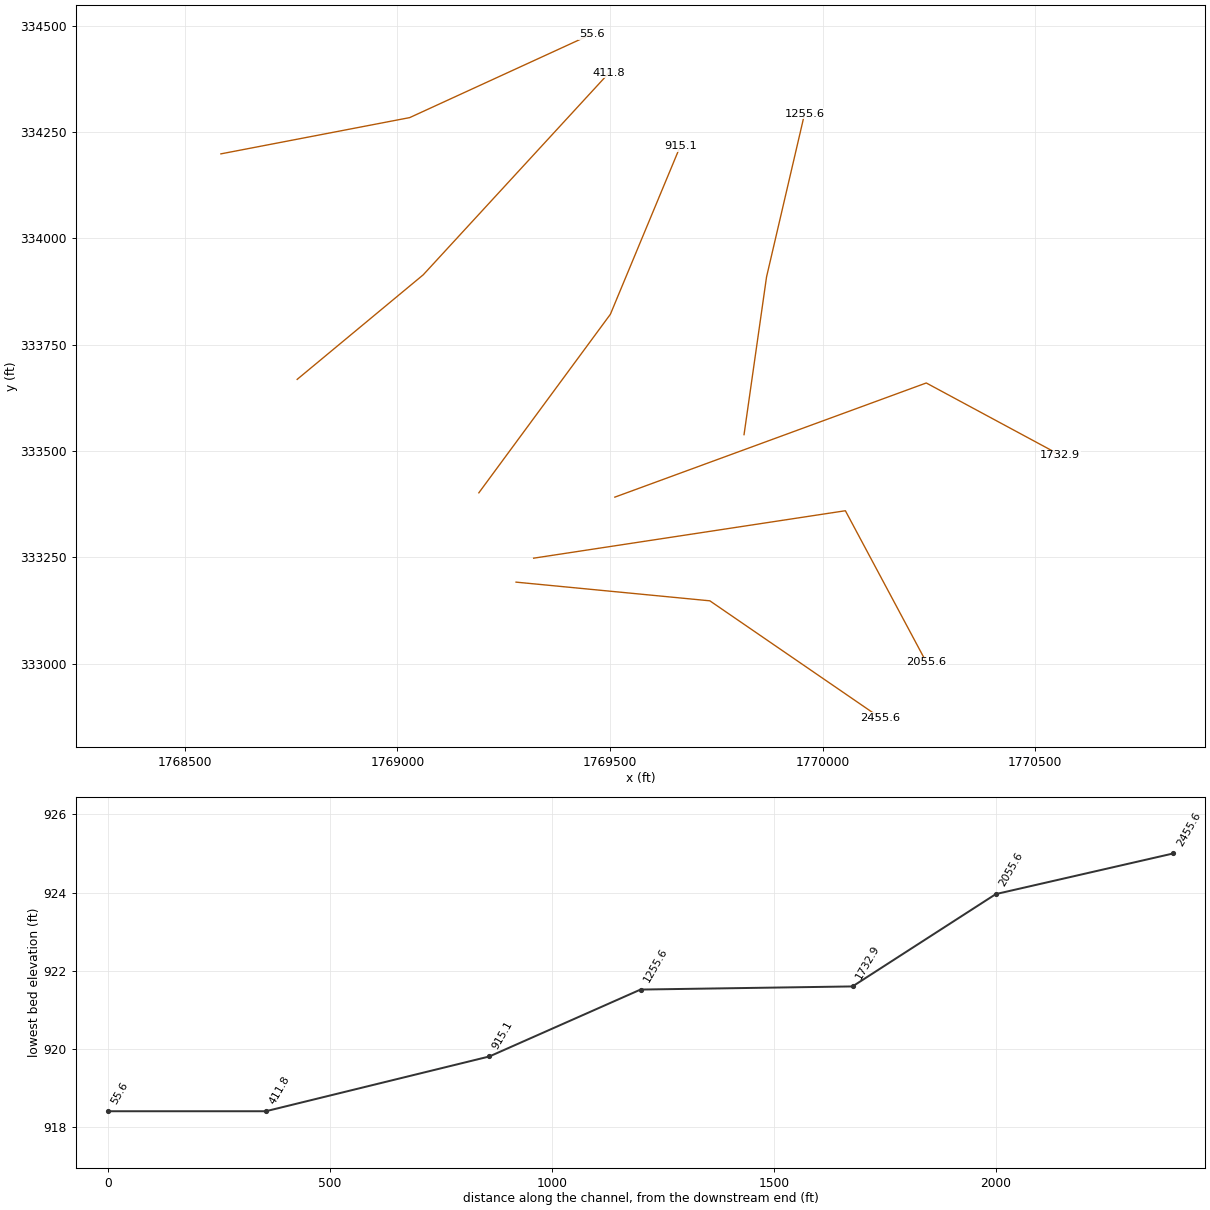
HEC-RAS study BthsRn1.prj: BthsRn1

--- BthsRn1.g01 (geometry) --- (continued)

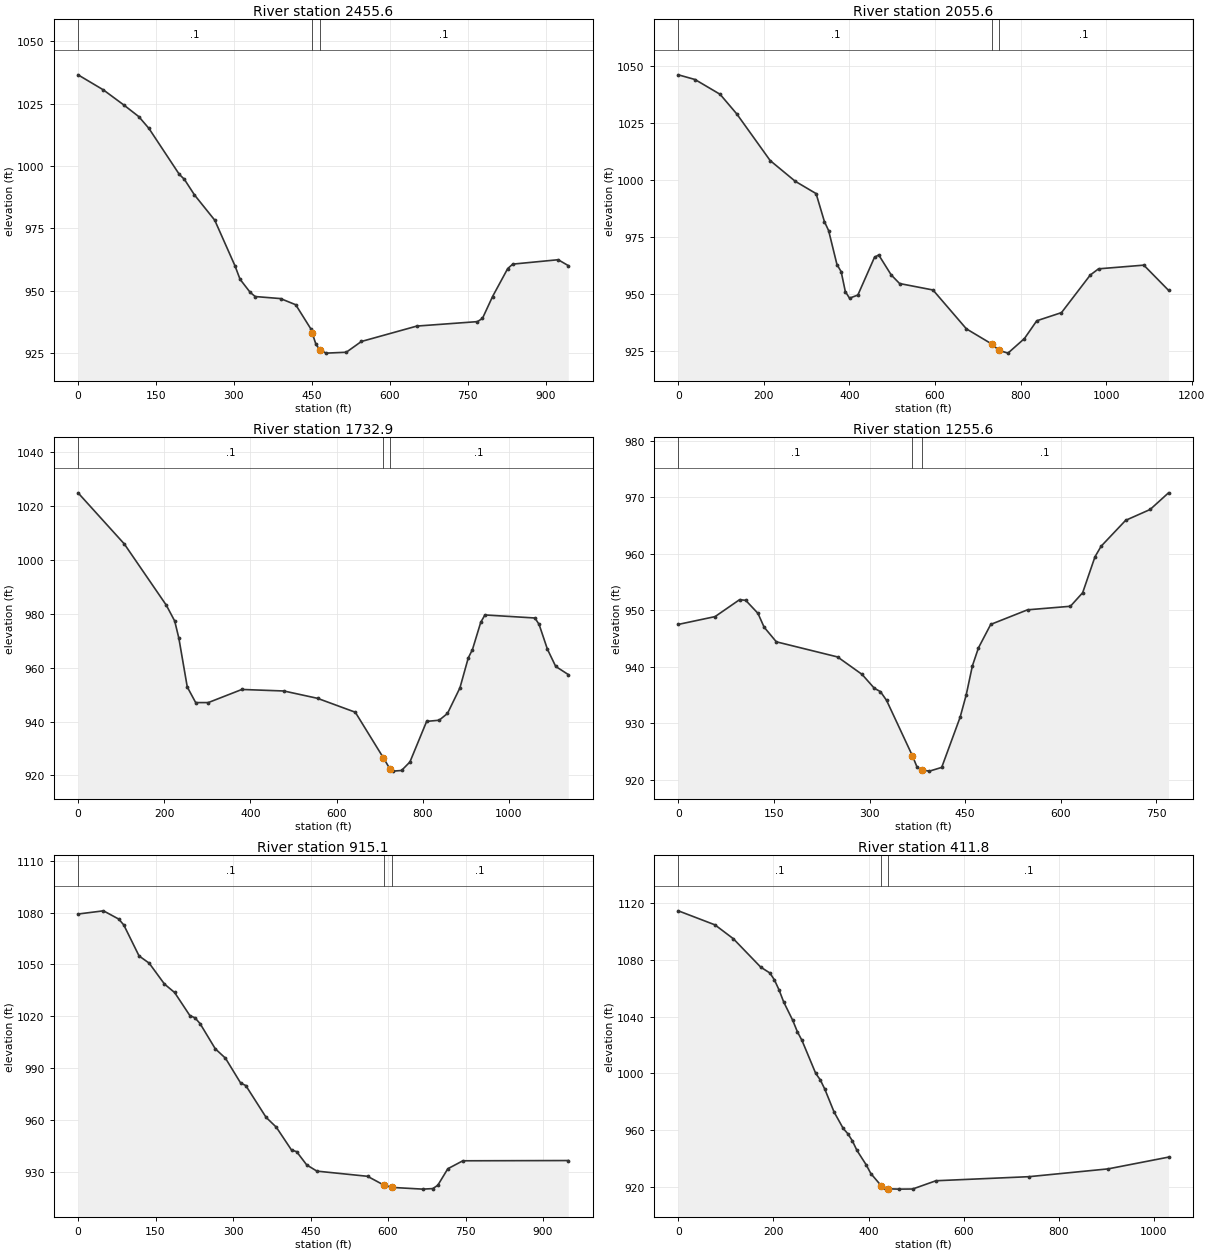
Type RM Length L Ch R = 1 ,2455.6  ,344.476,400,389.037
XS GIS Cut Line= 3
     1769278.805       333191.66     1769734.665      333147.707
     1770135.081      332872.884
#Sta/Elev= 30
       0 1036.59    48.7 1030.56    87.7 1024.56   116.9 1019.84   136.4 1015.11
   194.9  996.68   204.6  994.71   224.1  988.44   263.1  978.31   302.1     960
   311.8  954.63   331.3  949.37     341  947.69   389.8  946.87     419   944.4
   448.2  934.68   450.5  933.22     458  928.48   465.5  926.36   477.4     925
   516.3  925.35   545.4  929.67   652.2  935.85   768.8  937.63   778.5  938.95
   797.9  947.69   827.1  958.92   836.8  960.69   924.2  962.45   943.6   960.1
#Mann= 3 , 0 , 0
       0      .1       0   450.5    .045       0   465.5      .1       0
Bank Sta=450.5,465.5
XS Rating Curve= 0 ,0
Exp/Cntr=0.3,0.1

Type RM Length L Ch R = 1 ,2055.6  ,368.252,322.67,355.2
XS GIS Cut Line= 3
     1769320.263         333248.     1770053.415      333359.555
      1770243.95      333003.089
#Sta/Elev= 30
       0 1046.18      39 1044.12    97.6 1037.63   136.6 1029.01   214.7 1008.52
   273.2  999.44     322  994.02   341.5  981.69   351.3  977.77   370.8  962.84
   380.6  959.75   390.3  951.01   400.1   948.1   419.6  949.46   458.6  966.08
   468.4  967.07   497.6  958.29   517.2  954.52   595.2  951.69   673.3  934.62
   734.1   927.8   749.1  925.18   770.5  923.96     809  930.37   837.8  938.17
   895.6  941.75   962.9  958.27   982.2  960.98    1088   962.6  1145.8  951.54
#Mann= 3 , 0 , 0
       0      .1       0   734.1    .045       0   749.1      .1       0
Bank Sta=734.1,749.1
XS Rating Curve= 0 ,0
Exp/Cntr=0.3,0.1

Type RM Length L Ch R = 1 ,1732.9  ,452.745,477.331,499.931
XS GIS Cut Line= 3
     1769511.246      333391.553     1770243.641       333660.04
     1770558.582      333490.456
#Sta/Elev= 30
       0 1024.88   107.3 1005.92   204.8  983.19   224.3  977.32     234  970.92
   253.5  952.83     273  947.04   302.3  947.04   380.3  951.91   477.8  951.34
   555.8  948.62   643.5  943.46   708.8  926.51   723.8  922.45   731.3   921.6
   750.8  921.84   770.3     925   809.1  940.06   838.1  940.49   857.4  942.99
   886.4  952.51   905.7  963.61   915.4   966.7   934.7  976.84   944.4  979.56
  1060.4  978.43  1070.1  976.05  1089.4  966.86  1108.7  960.45  1137.8  957.45
#Mann= 3 , 0 , 0
       0      .1       0   708.8    .045       0   723.8      .1       0
Bank Sta=708.8,723.8
XS Rating Curve= 0 ,0
Exp/Cntr=0.3,0.1

Type RM Length L Ch R = 1 ,1255.6  ,348.043,340.416,334.773
XS GIS Cut Line= 3
     1769815.085      333538.464     1769867.983      333909.359
     1769957.498      334293.268
#Sta/Elev= 30
       0  947.49    57.6  948.87    96.1  951.87   105.7  951.75   124.9  949.45
   134.5  947.01   153.7  944.41   249.8  941.73   288.2  938.64   307.4  936.19
     317  935.59   326.6  934.05   367.1  924.25   374.6  922.19   382.1  921.71
   393.9  921.52   413.1  922.18     442  931.06   451.6  935.04   461.2  940.14
   470.8  943.35     490  947.49   547.7  950.07     615   950.7   634.2   953.1
   653.5  959.45   663.1  961.32   701.6  965.91     740  967.83   768.9  970.78
#Mann= 3 , 0 , 0
       0      .1       0   367.1    .045       0   382.1      .1       0
Bank Sta=367.1,382.1
XS Rating Curve= 0 ,0
Exp/Cntr=0.3,0.1

Type RM Length L Ch R = 1 ,915.1   ,508.661,503.35,498.039
XS GIS Cut Line= 3
     1769191.403      333401.738     1769500.703      333821.548
     1769664.835      334216.257
#Sta/Elev= 30
       0 1079.21    49.2 1081.06    78.7 1076.29    88.5 1072.89   118.1 1054.92
   137.7 1050.74   167.3 1038.62   186.9 1033.74   216.4 1020.39   226.3 1019.06
   236.1 1015.77   265.6 1001.13   285.3  995.69   314.8  981.26   324.7  979.83
     364   961.4   383.7  955.72   413.2  942.47   423.1  941.52   442.7  933.82
   462.4  930.24   560.3  927.25   592.4  922.08   607.4  920.81   667.2  919.81
   686.6  920.12   696.3  922.02   715.8  931.63   744.9  936.23   948.9  936.37
#Mann= 3 , 0 , 0
       0      .1       0   592.4    .045       0   607.4      .1       0
Bank Sta=592.4,607.4
XS Rating Curve= 0 ,0
Exp/Cntr=0.3,0.1

Type RM Length L Ch R = 1 ,411.8   ,371.54,356.235,346.444
XS GIS Cut Line= 3
     1768764.113      333668.502     1769060.593      333914.416
     1769497.722      334389.526
#Sta/Elev= 30
       0 1114.49      77 1104.61   115.6 1094.85   173.3 1074.81   192.6 1070.67
   202.2 1065.74   211.9 1058.68   221.5 1050.29   240.7 1037.23   250.4 1029.21
     260 1023.19   288.9  999.94   298.5   995.4   308.2  988.71   327.4  972.82
   346.7  961.15   356.3  957.51   365.9  952.47   375.6  945.68     395  935.55
   404.8  929.39   426.4  920.89   434.1  919.06   441.4  918.63   463.4  918.41
   492.8   918.5   541.7  924.31   737.3  927.18   903.6  932.67  1030.8  940.96
#Mann= 3 , 0 , 0
       0      .1       0   426.4    .045       0   441.4      .1       0
Bank Sta=426.4,441.4
XS Rating Curve= 0 ,0
Exp/Cntr=0.3,0.1

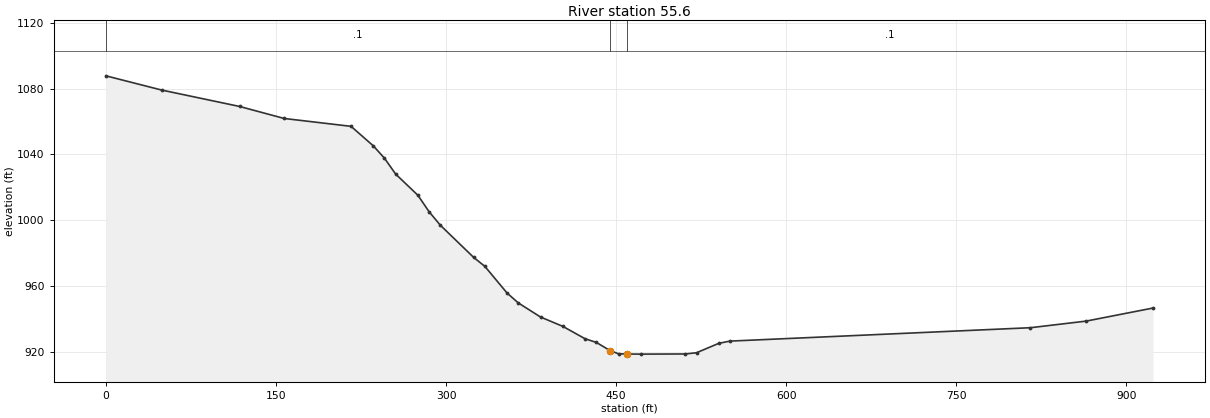
Type RM Length L Ch R = 1 ,55.6    ,55.554,55.554,50.039
XS GIS Cut Line= 3
     1768584.753      334198.869     1769028.753      334284.135
     1769457.179      334480.672
#Sta/Elev= 30
       0 1087.82    49.1 1079.17   117.9 1069.17   157.3 1061.85   216.2 1057.07
   235.9 1045.16   245.7 1037.65   255.5 1028.05   275.2 1015.07     285 1005.12
   294.9  996.91   324.3  977.31   334.2  971.85   353.8  955.59   363.7  949.58
   383.3     941     403   935.3   422.6  927.77   432.5  925.54   444.6  920.59
   452.1   918.6   459.6  918.48   471.8  918.41     511  918.51   520.9  919.25
   540.5  924.98   550.3  926.33   815.4  934.49   864.5  938.51   923.5  946.47
#Mann= 3 , 0 , 0
       0      .1       0   444.6    .045       0   459.6      .1       0
Bank Sta=444.6,459.6
XS Rating Curve= 0 ,0
Exp/Cntr=0.3,0.1

Chan Stop Cuts=-1
Use User Specified Reach Order=0